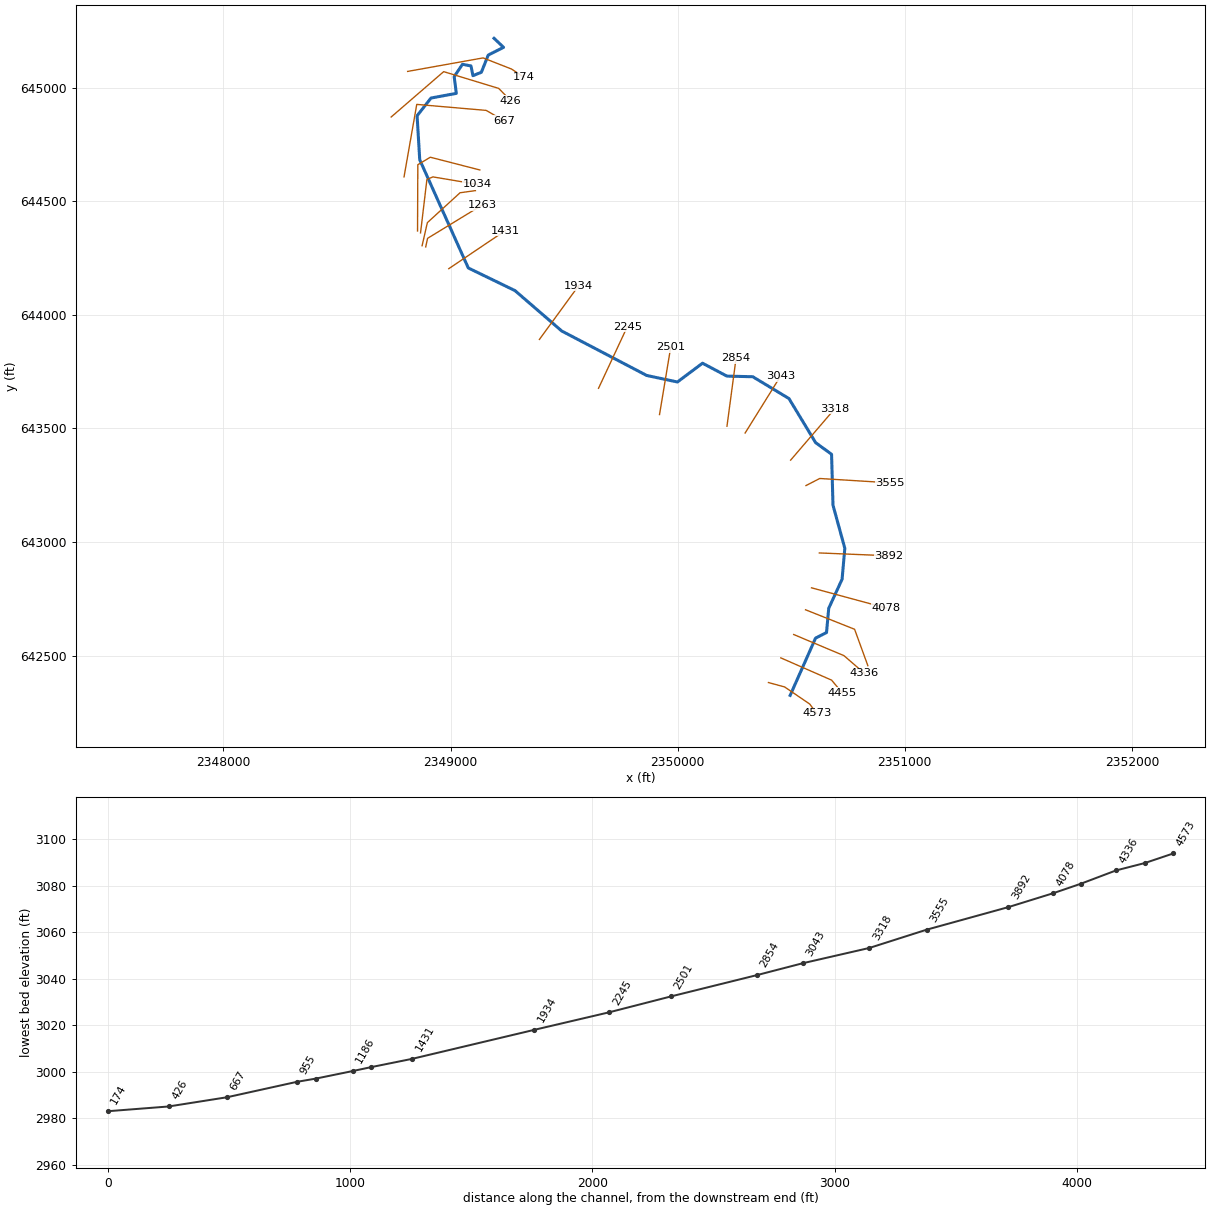
--- ADMSNRN.prj (project) ---

Proj Title=ADMSNRN
Current Plan=p01
Default Exp/Contr=0,0
English Units
Geom File=g01
Flow File=f01
Plan File=p01
BEGIN DESCRIPTION:
----------MODEL BY WOOD PLC 2022----------
AFH study
Randolph County, WV
HEC-RAS Version: RAS 6.2
Vertical Datum: NAVD88
Projection: NAD 1983 StatePlane West Virginia S FIPS 4702 (US Feet)
Terrain: 1-meter LIDAR (FEMA Region III 3DEP collected 2016-2018)
Land Use: 2019 NLCD
Hydrologic Method:
WV SIR2010-5033 regression equations
Additional Model Notes:
Left overbank on XS 743 and 875 do not visually tie-in needs to be fixed by mapping
END DESCRIPTION:
DSS Export Rating Curves= 0
DSS Export Rating Curve Sorted= 0
DSS Export Volume Flow Curves= 0
DXF OffsetX= 0
DXF OffsetY= 0
DXF ScaleX= 0
DXF ScaleY= 0

--- ADMSNRN.p01 (plan) ---

Plan Title=Floodplain
Program Version=6.20
Short Identifier=Floodplain
Geom File=g01
Flow File=f01
Subcritical Flow
K Sum by GR= 0
Std Step Tol= 0.01
Critical Tol= 0.01
Num of Std Step Trials= 20
Max Error Tol= 0.3
Flow Tol Ratio= 0.001
Split Flow NTrial= 30
Split Flow Tol= 0.02
Split Flow Ratio= 0.02
Log Output Level= 0
Friction Slope Method= 1
Unsteady Friction Slope Method= 2
Unsteady Bridges Friction Slope Method= 1
Parabolic Critical Depth
Global Vel Dist= 0 , 0 , 0
Global Log Level= 0
CheckData=True
Encroach Param=-1 ,0,0, 0
Mapping Interval=1HOUR
Computation Time Step Use Courant=        0
Computation Time Step Use Time Series=    0
Computation Time Step Count To Double=0
Computation Time Step Max Doubling=0
Computation Time Step Max Halving=0
Computation Time Step Residence Courant=0
Run HTab= 0
Run UNet= 0
Run Sediment= 0
Run PostProcess= 0
Run WQNet= 0
Run RASMapper=-1
UNET Theta= 0
UNET Theta Warmup= 0
UNET ZTol= 0
UNET ZSATol= 0
UNET MxIter= 0
UNET Max Iter WO Improvement= 0
UNET MaxInSteps= 0
UNET DtIC= 0
UNET DtMin= 0
UNET MaxCRTS= 0
UNET WFStab= 0
UNET SFStab= 0
UNET WFX= 1
UNET SFX= 1
UNET Gravity=32.174
UNET 1D Methodology=Finite Difference
UNET DSS MLevel= 1
UNET Pardiso=0
UNET DZMax Abort= 0
UNET Use Existing IB Tables= 0
UNET Froude Reduction=False
UNET Froude Limit= 0
UNET Froude Power= 0
UNET D1 Cores= 0
UNET WindReference=Eulerian
UNET WindDragFormulation=Hsu (1988)
UNET D2 Coriolis=0
UNET D2 Cores= 0
UNET D2 Theta= 1
UNET D2 Theta Warmup= 1
UNET D2 Z Tol= 0.01
UNET D2 Volume Tol= 0.01
UNET D2 Max Iterations= 20
UNET D2 Equation= 0
UNET D2 RampUpFraction=0.1
UNET D2 TimeSlices= 1
UNET D2 Turbulence Formulation=Non-Conservative (original)
UNET D2 Eddy Viscosity=0.3
UNET D2 Transverse Eddy Viscosity=0.1
UNET D2 Smagorinsky Mixing=0
UNET D2 BCVolumeCheck=0
UNET D2 Cores=0
UNET D2 SolverType=PARDISO (Direct)
UNET D2 Minimum Iterations= 2147483647
UNET D2 Maximum Iterations= 2147483647
UNET D2 Restart Number= 10
UNET D2 Relaxation Coeff=1.3
UNET D2 SOR Precondition Iterations= 10
UNET D2 ILUT Maximum Fill= 8
UNET D2 ILUT Tolerance=1E-08
UNET D1D2 MaxIter= 0
UNET D1D2 ZTol=0.01
UNET D1D2 QTol=0.1
UNET D1D2 MinQTol=1
Write IC File= 0
Write IC File at Fixed DateTime=0
Write IC File at Sim End=0
Echo Input=False
Echo Parameters=False
Echo Output=False
Write Detailed= 0
HDF Write Warmup=0
HDF Write Time Slices=0
HDF Flush=0
HDF Compression= 1
HDF Chunk Size= 1
HDF Spatial Parts= 1
HDF Use Max Rows=0
HDF Fixed Rows= 1
Calibration Method= 0
Calibration Iterations= 20
Calibration Max Change=0.05
Calibration Tolerance=0.2
Calibration Maximum=1.5
Calibration Minimum=0.5
Calibration Optimization Method= 1
WQ AD Non Conservative
WQ ULTIMATE=-1
WQ Max Comp Step=1HOUR
WQ Output Interval=15MIN
WQ Output Selected Increments= 0
WQ Output face flow=0
WQ Output face velocity=0
WQ Output face area=0
WQ Output face dispersion=0
WQ Output cell volume=0
WQ Output cell surface area=0
WQ Output cell continuity=0
WQ Output cumulative cell continuity=0
WQ Output face conc=0
WQ Output face dconc_dx=0
WQ Output face courant=0
WQ Output face peclet=0
WQ Output face adv mass=0
WQ Output face disp mass=0
WQ Output cell mass=0
WQ Output cell source sink temp=0
WQ Output nsm pathways=0
WQ Output nsm derived pathways=0
WQ Create Restart=0
WQ Fixed Restart=0
WQ System Summary=0
WQ Write To DSS=0
Sorting and Armoring Iterations= 10
XS Update Threshold= 0.02
Bed Roughness Predictor= 0
Hydraulics Update Threshold= 0.02
Energy Slope Method= 1
Volume Change Method= 1
Sediment Retention Method= 0
Sediment TS Multiplier= 1
Warm Up Method= 0
XS Weighting Method= 0
Number of US Weighted Cross Sections= 1
Number of DS Weighted Cross Sections= 1
Upstream XS Weight=0
Main XS Weight=1
Downstream XS Weight=0
Number of DS XS's Weighted with US Boundary= 1
Upstream Boundary Weight= 1
Weight of XSs Associated with US Boundary= 0
Number of US XS's Weighted with DS Boundary= 1
Downstream Boundary Weight= 0.5
Weight of XSs Associated with DS Boundary= 0.5
Percentile Method= 0
Sediment Output Level= 3
Mass or Volume Output= 0
Output Increment Type= 1
Profile and TS Output Increment= 1
Transport Output Increment 1
XS Output Flag= 0
XS Output Increment= 10
Read HDF5 Sediment Hotstart= 0
Sediment Hotstart Type= 0
Write Gradation File= 0
Read Gradation Hotstart= 0
Write HDF5 File= 1
Write Binary Output= 1
Write DSS Sediment File= 0
DSS Sediment Output Type= 1
SV Curve= 0
Specific Gage Flag= 0
Subcell Erosion Methods= 0
Subcell Deposition Methods= 0
Advection Scheme= 1
Matrix Solver= 0
Implicit Weighting Factor= 1
Maximum Outer Loop Convergence Iterations= 5
Convergence Maximum Absolute= 0.001
Convergence RMSE= 0.0001
Grain Fractions Max Abs Error= 0.001
Max Subgrid Regions= 1
Max Subgrid Length Scale= 3.402823E+38
Initial Layer Thickness= 3.402823E+38
Min Layer Thickness= 3.402823E+38
Max Layer Thickness= 3.402823E+38
Number of Layers= 5

--- ADMSNRN.f01 (steady flow) ---

Flow Title=Flow
Program Version=6.20
Number of Profiles= 1
Profile Names=P100yr
River Rch & RM=ADMSNRN,Main,4573
     493
Boundary for River Rch & Prof#=ADMSNRN,Main            , 1
Up Type= 0
Dn Type= 3
Dn Slope=0.00938
DSS Import GetInterval= 0
DSS Import GetPeak= 0
DSS Import FillOption= 0

--- ADMSNRN.g01 (geometry) ---

Geom Title=Geometry
Program Version=6.20

River Reach=ADMSNRN         ,Main
Reach XY= 30
       2350495.3      642324.8072350606.99527327 642576.70773209
 2350655.3818995642601.481576612     2350665.091       642708.14
     2350723.945      642836.265     2350735.924      642972.398
     2350683.841      643162.307     2350677.591      643386.265
 2350607.4221567      643437.451     2350489.963      643631.719
     2350330.664      643727.697     2350216.654      643730.536
     2350109.362      643787.3072349998.72829715643704.666542756
  2349863.622093643733.3476497992349489.58905701643929.028108551
       2349283.8      644106.836     2349078.112      644206.577
2348864.30390831644682.798302397     2348852.591       644876.89
2348914.00207594644954.8861590392349025.36793288644975.441243789
     2349015.945      645049.105     2349052.403      645103.496
     2349089.903      645096.204     2349098.597      645053.396
2349135.41497364645068.172851735     2349165.945      645144.121
     2349233.306      645178.149     2349191.521      645217.745

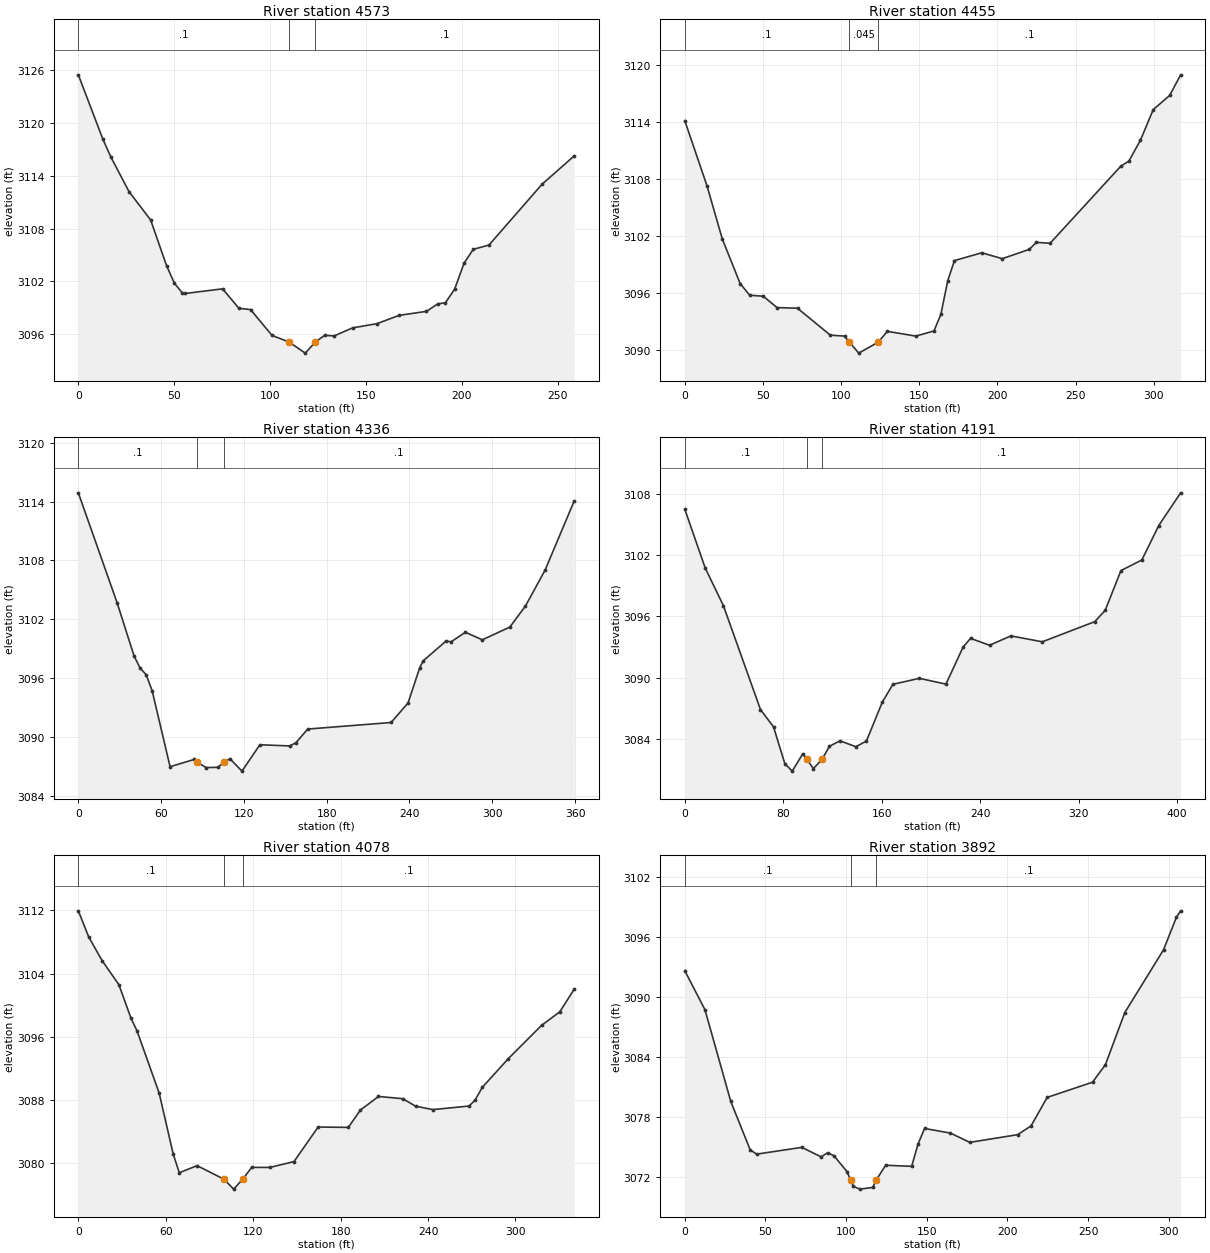
Type RM Length L Ch R = 1 ,4573    ,117.3,118.5,120
XS GIS Cut Line= 4
2350399.80042279642381.2182016422350470.78613466642361.907990306
2350581.43729099642286.556589371 2350611.8382414642245.479751009
#Sta/Elev= 30
       0 3125.48    12.8 3118.16      17 3116.12    26.4 3112.21    37.7 3108.98
      46 3103.78    50.1 3101.78    54.3 3100.67    55.7 3100.62    75.2 3101.15
    83.7 3098.94    89.8 3098.79     101 3095.85  109.89  3095.1   118.3 3093.84
  123.563095.099   128.5 3095.87   133.3 3095.79     143 3096.71   155.7 3097.19
   167.2 3098.13   181.5 3098.59   187.4 3099.44   191.4 3099.57   196.2 3101.12
   201.1 3104.06   205.9 3105.64   214.1 3106.13   241.8 3113.05   258.5 3116.26
#Mann= 3, -1 ,  0
       0     0.1       0  109.89   0.045       0  123.56     0.1       0
Bank Sta=109.89,123.56
XS Rating Curve= 0 ,0
Exp/Cntr(USF)=0,0
Exp/Cntr=0.3,0.1

Type RM Length L Ch R = 1 ,4455    ,118.7,118.9,118.9
XS GIS Cut Line= 3
2350454.17439049642489.8508572622350677.83277687  642391.7770141
2350724.63147368642335.814613492
#Sta/Elev= 30
       0 3114.13    14.2 3107.28      24 3101.69    35.4 3097.01    41.5 3095.78
    50.2 3095.67      59 3094.48    72.1 3094.41    93.1 3091.58   102.2 3091.48
  105.313090.837   111.3 3089.69  123.663090.837   129.6 3091.98   147.8 3091.48
   159.4 3092.02   163.8 3093.76   168.2 3097.29   172.5 3099.42     190 3100.24
   203.1 3099.62   220.4  3100.6   224.9 3101.34   233.7 3101.24   278.9 3109.34
   284.1 3109.88   291.5 3112.08   299.7  3115.3   310.2 3116.78   317.2 3118.95
#Mann= 3, -1 ,  0
       0     0.1       0  105.31   0.045       0  123.66     0.1       0
Bank Sta=105.31,123.66
XS Rating Curve= 0 ,0
Exp/Cntr(USF)=0,0
Exp/Cntr=0.3,0.1

Type RM Length L Ch R = 1 ,4336    ,144.1,145.1,142.1
XS GIS Cut Line= 3
2350510.83778021642592.7140832612350732.14009286642499.712804629
 2350822.4260057642421.646037894
#Sta/Elev= 30
       0 3114.89    28.2 3103.64    40.4 3098.25    44.8 3097.01    49.2 3096.34
    53.5 3094.71    66.5 3086.96    83.9  3087.7    86.2 3087.42    92.6 3086.87
   101.2  3086.9   105.6 3087.41   109.9 3087.78   118.6 3086.51   131.6  3089.2
   153.1 3089.08   157.6 3089.39   166.3  3090.8   226.7 3091.47     239 3093.46
   247.5 3097.07     250 3097.76   266.5 3099.77   270.2  3099.7   280.6 3100.67
   292.8  3099.9   312.8  3101.2   324.1 3103.35   338.3    3107   359.4 3114.05
#Mann= 3, -1 ,  0
       0     0.1       0    86.2   0.045       0   105.6     0.1       0
Bank Sta=86.2,105.6
XS Rating Curve= 0 ,0
Exp/Cntr(USF)=0,0
Exp/Cntr=0.3,0.1

Type RM Length L Ch R = 1 ,4191    ,112.6,113.2,114
XS GIS Cut Line= 3
2350563.02277776642701.639120808 2350778.9801529642615.794692556
2350837.36051759642455.588110388
#Sta/Elev= 30
       0 3106.54    16.6 3100.76    31.4 3097.05    61.5 3086.85    72.1 3085.15
    81.3 3081.53    87.3  3080.8    95.9 3082.51   99.123081.963   104.5 3081.05
  111.523081.952   117.5 3083.24   126.1 3083.78     139  3083.2   147.6 3083.76
   160.5 3087.58   169.1 3089.33   190.6 3089.92   212.2 3089.35   226.1 3092.98
   232.2 3093.85   247.6 3093.17     265 3094.09   290.5 3093.51   333.1 3095.49
   341.6  3096.6   354.4 3100.51   371.4 3101.55   385.1 3104.93   402.9 3108.15
#Mann= 3, -1 ,  0
       0     0.1       0   99.12   0.045       0  111.52     0.1       0
Bank Sta=99.12,111.52
XS Rating Curve= 0 ,0
Exp/Cntr(USF)=0,0
Exp/Cntr=0.3,0.1

Type RM Length L Ch R = 1 ,4078    ,183.7,185.7,187.1
XS GIS Cut Line= 2
2350589.30228845642798.3340557612350917.76787246642709.368003192
#Sta/Elev= 30
       0 3111.93     7.1 3108.64    16.3 3105.64    27.8 3102.61    36.1 3098.38
    40.3 3096.75    55.5 3088.88    65.1  3081.2    69.3 3078.83    81.5 3079.73
   99.883078.019   106.6 3076.76  112.843078.017     119 3079.51   131.4  3079.5
     148 3080.24   164.6 3084.61   185.3 3084.56   193.6 3086.75     206 3088.47
   222.6 3088.19   231.5 3087.24   243.3 3086.81   268.2 3087.26   272.3 3088.01
   277.2 3089.61   295.1 3093.25   317.9 3097.45   330.4 3099.16   340.3 3102.02
#Mann= 3, -1 ,  0
       0     0.1       0   99.88   0.045       0  112.84     0.1       0
Bank Sta=99.88,112.84
XS Rating Curve= 0 ,0
Exp/Cntr(USF)=0,0
Exp/Cntr=0.3,0.1

Type RM Length L Ch R = 1 ,3892    ,337.8,336.8,336.2
XS GIS Cut Line= 2
2350623.72947367 642951.878007322350930.82016741642939.405936211
#Sta/Elev= 30
       0 3092.63    12.5 3088.72    28.5 3079.54    40.5 3074.71    44.5 3074.27
    72.5 3074.95    84.5    3074    88.5 3074.41    92.5  3074.1   100.5 3072.53
  102.793071.677   104.5 3071.04   108.5 3070.77   116.5 3070.94  118.623071.679
   124.5 3073.16   140.6 3073.05   144.6  3075.3   148.6 3076.84   164.6 3076.38
   176.6 3075.45   206.3 3076.22   214.6  3077.1   224.6 3079.95   252.7 3081.47
   260.7 3083.23   272.7 3088.44   296.7 3094.72   304.7 3097.98   307.3 3098.62
#Mann= 3, -1 ,  0
       0     0.1       0  102.79   0.045       0  118.62     0.1       0
Bank Sta=102.79,118.62
XS Rating Curve= 0 ,0
Exp/Cntr(USF)=0,0
Exp/Cntr=0.3,0.1

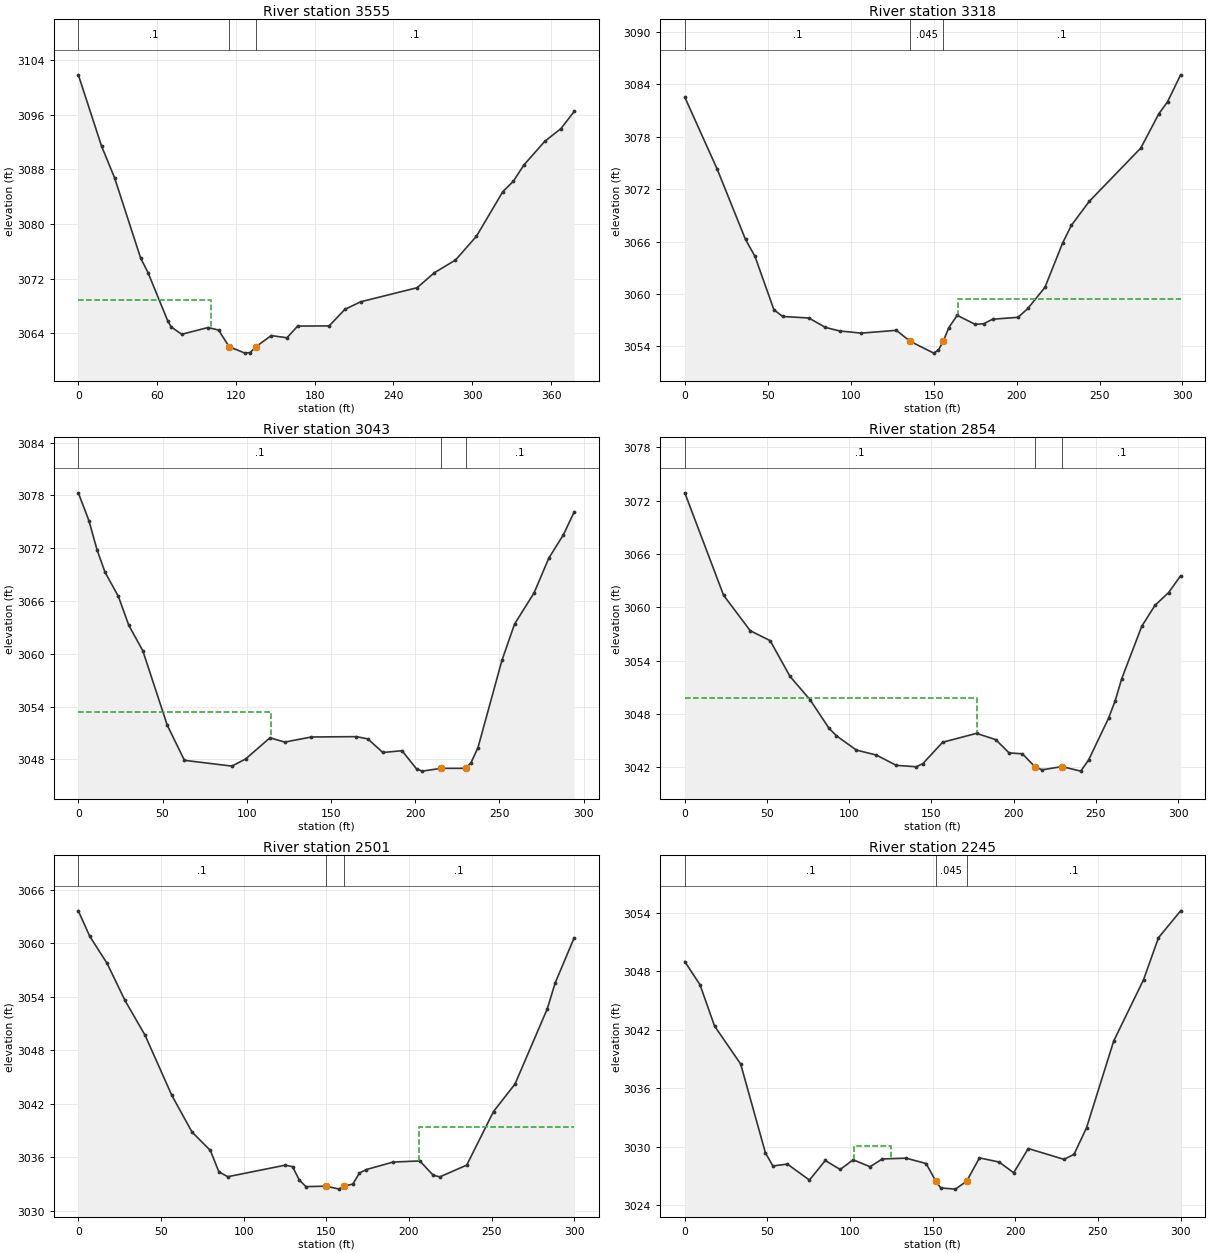
Type RM Length L Ch R = 1 ,3555    ,226,237,244.7
XS GIS Cut Line= 3
2350564.94178539643248.5549534492350625.56198523643279.701630528
2350934.43484492643260.694069932
#Sta/Elev= 30
       0 3101.85    17.7  3091.4    27.6 3086.77    47.4 3075.04    53.1 3072.87
    68.2 3065.76    70.8 3064.91    78.8 3063.85    98.8 3064.84   106.8 3064.47
  114.843062.031   126.9 3061.09   130.9 3061.18  135.27 3062.03   146.9 3063.66
   158.9 3063.34     167 3065.05     191 3065.08     203  3067.5     215 3068.61
     258 3070.67   271.1 3072.86   287.2 3074.72   303.2 3078.21   323.2 3084.72
   331.3 3086.27   339.3 3088.64   355.3 3092.13   367.5 3093.97   377.6 3096.48
#Mann= 3, -1 ,  0
       0     0.1       0  114.84   0.045       0  135.27     0.1       0
#XS Ineff= 2 , 0
          100.85 3068.86
Permanent Ineff=
       F       F
Bank Sta=114.84,135.27
XS Rating Curve= 0 ,0
Exp/Cntr(USF)=0,0
Exp/Cntr=0.3,0.1

Type RM Length L Ch R = 1 ,3318    ,273.8,275.1,275.1
XS GIS Cut Line= 2
2350497.26095121643360.4837630622350692.08844732643587.216807318
#Sta/Elev= 30
       0 3082.53    19.6 3074.26    36.6 3066.24    42.3 3064.31    53.7 3058.21
    58.9 3057.43    74.8 3057.25    84.8 3056.17    93.3 3055.77   106.4 3055.52
   127.5 3055.84  135.833054.588   150.1 3053.23   152.9 3053.59  155.823054.588
   159.1 3056.13   164.2 3057.56     175 3056.53   180.2 3056.59   185.5 3057.11
   200.9 3057.33   206.8 3058.34   217.1 3060.76   227.7 3065.81     233 3067.85
   243.8  3070.6   274.9 3076.71   285.7 3080.61     291    3082   298.9 3085.09
#Mann= 3, -1 ,  0
       0     0.1       0  135.83   0.045       0  155.82     0.1       0
#XS Ineff= 2 , 0
                          164.88         3059.48
Permanent Ineff=
       F       F
Bank Sta=135.83,155.82
XS Rating Curve= 0 ,0
Exp/Cntr(USF)=0,0
Exp/Cntr=0.3,0.1

Type RM Length L Ch R = 1 ,3043    ,185.4,188.7,191.9
XS GIS Cut Line= 2
 2350296.8805008643479.7329957872350452.53865535643729.603077576
#Sta/Elev= 30
       0 3078.29     6.3 3075.12    11.1 3071.82    15.8 3069.29    23.8 3066.51
      30 3063.22    38.3 3060.34    52.8 3051.88      63 3047.89    91.2 3047.23
    99.3 3048.04   113.8 3050.45   122.5 3049.96   138.4 3050.54   165.1 3050.58
   171.9 3050.32   180.8 3048.78   192.2 3048.98   200.9 3046.89   204.3 3046.66
   215.4 3046.98  229.98 3046.98   233.2 3047.63   237.3 3049.34   251.5 3059.24
     259 3063.37   270.6 3066.92   279.3 3070.85     288 3073.52   294.4 3076.11
#Mann= 3, -1 ,  0
       0     0.1       0   215.4   0.045       0  229.98     0.1       0
#XS Ineff= 2 , 0
          114.15  3053.4
Permanent Ineff=
       F       F
Bank Sta=215.4,229.98
XS Rating Curve= 0 ,0
Exp/Cntr(USF)=0,0
Exp/Cntr=0.3,0.1

Type RM Length L Ch R = 1 ,2854    ,352.3,353.5,353.1
XS GIS Cut Line= 2
2350217.06794813643509.7485481812350256.98030052643808.610720066
#Sta/Elev= 30
       0 3072.88    23.6 3061.35    39.8 3057.37    51.9 3056.25      64 3052.22
    76.1 3049.62    87.7 3046.39    92.2 3045.55   104.3 3043.94   116.5 3043.38
   128.6 3042.22   140.7 3042.06   144.7 3042.41   156.8 3044.82   177.4 3045.82
   189.1 3045.11   197.2 3043.62   205.3 3043.52   212.9 3042.06   217.3 3041.72
   229.4 3042.08   240.8 3041.57   245.6 3042.85   257.7 3047.53   261.7 3049.48
   265.7 3051.98   277.9 3057.88   285.9 3060.22   294.2 3061.66   301.5 3063.55
#Mann= 3, -1 ,  0
       0     0.1       0   212.9   0.045       0   229.4     0.1       0
#XS Ineff= 2 , 0
          177.47 3049.76
Permanent Ineff=
       F       F
Bank Sta=212.9,229.4
XS Rating Curve= 0 ,0
Exp/Cntr(USF)=0,0
Exp/Cntr=0.3,0.1

Type RM Length L Ch R = 1 ,2501    ,256.1,255.2,253.6
XS GIS Cut Line= 2
2349920.03999795643561.3390696362349969.29530307643857.267971431
#Sta/Elev= 30
       0 3063.62     6.9 3060.77    17.4 3057.74    28.2 3053.59    40.4 3049.68
    56.6 3042.94    68.8 3038.84    79.9 3036.78      85  3034.4    90.4 3033.84
   125.1 3035.13   129.6 3034.97   133.7 3033.47   137.7 3032.73   149.9 3032.78
     158 3032.45  160.65 3032.78   166.1 3033.02   170.1 3034.25   174.2 3034.64
   190.4 3035.48   206.6 3035.61   214.8 3033.99   218.8 3033.83     235 3035.14
   251.2 3041.14   264.2 3044.22   283.7 3052.63   288.5 3055.54     300  3060.6
#Mann= 3, -1 ,  0
       0     0.1       0   149.9   0.045       0  160.65     0.1       0
#XS Ineff= 2 , 0
                          206.05         3039.37
Permanent Ineff=
       F       F
Bank Sta=149.9,160.65
XS Rating Curve= 0 ,0
Exp/Cntr(USF)=0,0
Exp/Cntr=0.3,0.1

Type RM Length L Ch R = 1 ,2245    ,313.1,311.6,309.3
XS GIS Cut Line= 2
2349651.52178748643676.8674877312349778.44431052643948.695876873
#Sta/Elev= 30
       0    3049     9.2 3046.62      18 3042.38    33.8 3038.48    48.8 3029.35
    53.3 3028.01    62.1  3028.2    75.4 3026.56      85 3028.57      94 3027.65
   101.9 3028.64   112.1 3027.93   119.5 3028.73   133.9 3028.81     146 3028.26
  151.933026.438   154.9 3025.75   163.7 3025.63  170.543026.441   178.3 3028.84
   190.2 3028.41     199 3027.31   207.8  3029.8   229.4 3028.69   235.5  3029.2
   243.1 3031.95   259.5 3040.84   277.6 3047.15   286.6 3051.45     300 3054.21
#Mann= 3, -1 ,  0
       0     0.1       0  151.93   0.045       0  170.54     0.1       0
#XS Ineff= 1 ,-1
   102.6  124.65 3030.05
Permanent Ineff=
       F
Bank Sta=151.93,170.54
XS Rating Curve= 0 ,0
Exp/Cntr(USF)=0,0
Exp/Cntr=0.3,0.1

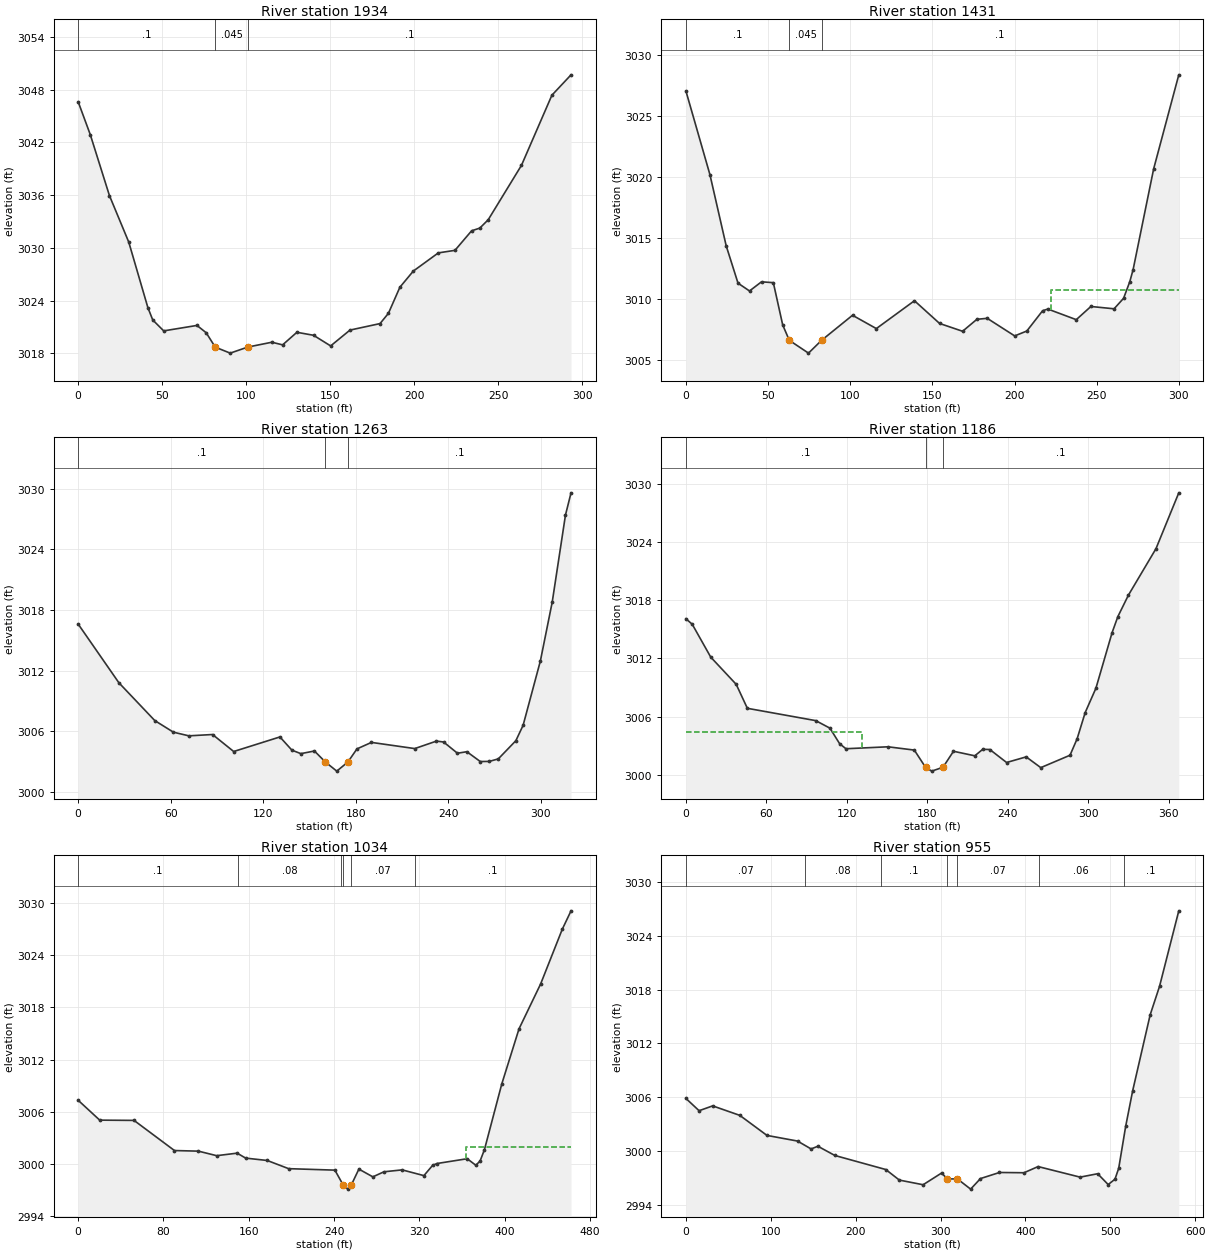
Type RM Length L Ch R = 1 ,1934    ,503.7,503,496.7
XS GIS Cut Line= 2
 2349391.2394004643892.0740635432349564.25879454644128.970373902
#Sta/Elev= 30
       0 3046.61     7.2 3042.88    18.6 3035.95    30.1 3030.66    41.5  3023.2
    44.4  3021.8    50.9 3020.56    70.7 3021.18    76.2 3020.35    81.6 3018.71
    90.5 3018.03     101 3018.72   115.3 3019.27   121.7 3018.97   130.2  3020.4
   140.1 3020.06   150.3 3018.85   161.8 3020.65   179.7 3021.39   184.7 3022.56
   191.5 3025.52   199.5 3027.36   214.4 3029.43   224.3 3029.72   234.2 3031.94
   239.1 3032.25   244.1  3033.2   263.9 3039.39     282 3047.36   293.4 3049.68
#Mann= 3, -1 ,  0
       0     0.1       0    81.6   0.045       0     101     0.1       0
Bank Sta=81.6,101
XS Rating Curve= 0 ,0
Exp/Cntr(USF)=0,0
Exp/Cntr=0.3,0.1

Type RM Length L Ch R = 1 ,1431    ,169.3,167.5,166.7
XS GIS Cut Line= 2
2348992.08507121644203.4852560332349240.89898217644371.090857705
#Sta/Elev= 30
       0 3027.06    14.6 3020.22    24.5 3014.39    31.7 3011.33    38.7 3010.69
      46 3011.44    53.2 3011.37    58.9 3007.91   62.913006.649    74.6  3005.6
   82.58 3006.65   101.4  3008.7   115.9 3007.61   139.1 3009.89   154.4 3008.03
   168.4 3007.39   177.1 3008.37   183.4 3008.45   200.1 3007.01   207.5 3007.41
   217.1 3009.07   220.3 3009.21   237.6 3008.34   246.5 3009.42   260.6 3009.23
   266.4 3010.09   270.2 3011.46   272.2 3012.44   284.7 3020.69     300 3028.39
#Mann= 3, -1 ,  0
       0     0.1       0   62.91   0.045       0   82.58     0.1       0
#XS Ineff= 2 , 0
                          221.99         3010.75
Permanent Ineff=
       F       F
Bank Sta=62.91,82.58
XS Rating Curve= 0 ,0
Exp/Cntr(USF)=0,0
Exp/Cntr=0.3,0.1

Type RM Length L Ch R = 1 ,1263    ,75.8,77,78.5
XS GIS Cut Line= 3
2348890.50643207644299.3276817332348898.76249218644337.123314034
2349138.77198171644483.571719984
#Sta/Elev= 30
       0 3016.62    26.4 3010.82    49.7 3007.08    61.8 3005.93    71.8 3005.57
    87.2  3005.7   100.9 3004.02   130.9 3005.46   138.7 3004.15   144.5 3003.81
   153.3 3004.07  160.373002.986   167.8 3002.08     175 3002.98   180.9 3004.28
   190.3 3004.92   218.4 3004.31   232.5 3005.05   237.1 3004.96   246.1 3003.85
   252.2    3004   260.9 3003.03   266.7 3003.04   272.6 3003.29     284 3005.09
   288.7 3006.61   299.9 3012.97   307.6  3018.8   316.2 3027.41   319.8  3029.6
#Mann= 3, -1 ,  0
       0     0.1       0  160.37   0.045       0     175     0.1       0
Bank Sta=160.37,175
XS Rating Curve= 0 ,0
Exp/Cntr(USF)=0,0
Exp/Cntr=0.3,0.1

Type RM Length L Ch R = 1 ,1186    ,154,152.4,149.1
XS GIS Cut Line= 4
2348874.66175904644304.5687102652348897.80368133644406.134190385
2349041.79591872644537.7915601082349109.38927719644547.243509135
#Sta/Elev= 30
       0  3016.1     4.7 3015.53    18.5 3012.14    37.5 3009.33    45.8 3006.86
    96.8 3005.59   107.4 3004.81   114.6 3003.21   119.3 3002.69   150.7 3002.89
   170.3 3002.55  178.64 3000.78   183.3 3000.38   191.7 3000.78   199.5 3002.43
   215.4 3001.96   221.3 3002.63   226.6 3002.61   239.1 3001.27   253.7 3001.85
   264.6 3000.74   286.4 3002.02   291.7 3003.72   297.7 3006.42   305.7 3008.93
   317.8 3014.68   322.1 3016.33     330 3018.55   350.5 3023.33   367.5 3029.09
#Mann= 3, -1 ,  0
       0     0.1       0  178.64   0.045       0   191.7     0.1       0
#XS Ineff= 2 , 0
          130.96 3004.42
Permanent Ineff=
       F       F
Bank Sta=178.64,191.7
XS Rating Curve= 0 ,0
Exp/Cntr(USF)=0,0
Exp/Cntr=0.3,0.1

Type RM Length L Ch R = 1 ,1034    ,78.5,79,79.8
XS GIS Cut Line= 4
2348867.82426552644361.1410127422348895.81660593 644596.29191559
2348922.38038912644607.6557481952349116.30732205644575.099211923
#Sta/Elev= 30
       0 3007.33    20.2 3005.05    52.4 3005.02    90.3 3001.56   112.8 3001.49
   129.9 3000.97   149.1 3001.26   157.1 3000.69   177.3 3000.42   197.4 2999.48
   240.8 2999.31  248.44 2997.63     253 2997.13  256.32 2997.64   263.3 2999.43
   276.4 2998.54   286.8 2999.12   303.9 2999.34   324.3 2998.68   332.4 2999.85
   336.5 3000.07   364.9 3000.62     373 2999.87     377 3000.36   381.1 3001.67
   397.3 3009.19   413.5 3015.53   433.8 3020.69   454.1 3026.97   462.3 3029.08
#Mann= 6, -1 ,  0
       0     0.1       0     150    0.08       0  246.81    0.07       0
  248.44   0.045       0  256.32    0.07       0   315.7     0.1       0
#XS Ineff= 2 , 0
                          363.51         3001.94
Permanent Ineff=
       F       F
Bank Sta=248.44,256.32
XS Rating Curve= 0 ,0
Exp/Cntr(USF)=0,0
Exp/Cntr=0.3,0.1

Type RM Length L Ch R = 1 ,955     ,288.9,288,280.4
XS GIS Cut Line= 4
 2348854.5990242644369.7021579142348855.81898442644661.271500706
2348910.79786566644694.3017480752349128.82369587644638.158069482
#Sta/Elev= 30
       0 3005.85    15.5 3004.48    31.5 3005.02    63.5 3003.96    95.5 3001.72
   131.5 3001.09   147.5 3000.21   155.5 3000.51   175.5 2999.48   235.5 2997.91
   251.5 2996.73   279.5 2996.21   301.3 2997.52  308.06 2996.86     320 2996.86
   335.5 2995.72   347.1  2996.9   369.5 2997.58   398.4 2997.55     415 2998.24
   464.5 2997.06   485.2 2997.44   497.6 2996.23   505.6 2996.83     510 2998.05
   518.2 3002.73   526.5 3006.73   547.1  3015.2   558.1 3018.37   580.8 3026.81
#Mann= 7, -1 ,  0
       0    0.07       0     140    0.08       0     230     0.1       0
  308.06   0.045       0     320    0.07       0  415.71    0.06       0
  515.71     0.1       0
Bank Sta=308.06,320
XS Rating Curve= 0 ,0
Exp/Cntr(USF)=0,0
Exp/Cntr=0.3,0.1

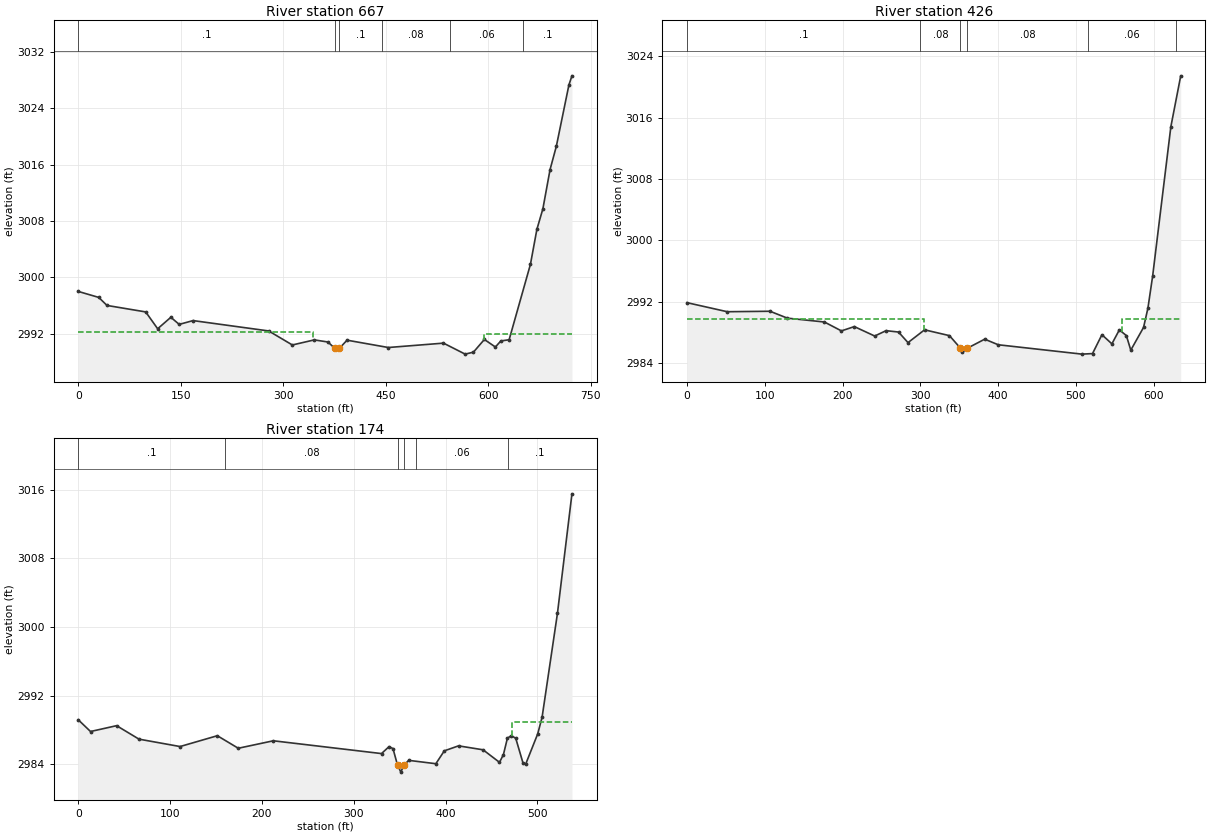
Type RM Length L Ch R = 1 ,667     ,239,241.2,239
XS GIS Cut Line= 4
 2348795.1213145644607.6720062842348851.12322772644926.882911662
2349156.73366846644900.4820097142349235.93637431644854.880451802
#Sta/Elev= 30
       0 2998.01      30 2997.16    42.1 2996.02    98.7  2995.1   116.2 2992.71
   135.5 2994.34   147.7 2993.33     168 2993.87   278.6  2992.4   313.2 2990.41
   345.3 2991.13   365.3 2990.83  375.31 2989.93   382.1 2989.94   393.2 2991.09
   453.6 2990.05   534.3 2990.67     566 2989.11   578.1 2989.39   594.1 2991.19
   610.2 2990.12   618.2 2990.98   630.3 2991.15   661.5 3001.86   670.9 3006.81
   679.7 3009.74   690.2 3015.31   699.4 3018.62   717.8 3027.33   722.2 3028.61
#Mann= 6, -1 ,  0
       0     0.1       0  375.31   0.045       0   382.1     0.1       0
  444.09    0.08       0  544.09    0.06       0  650.83     0.1       0
#XS Ineff= 2 , 0
           343.7 2992.18  593.22         2991.98
Permanent Ineff=
       F       F
Bank Sta=375.31,382.1
XS Rating Curve= 0 ,0
Exp/Cntr(USF)=0,0
Exp/Cntr=0.3,0.1

Type RM Length L Ch R = 1 ,426     ,250.9,251.2,248.2
XS GIS Cut Line= 4
2348738.52901156644871.3905177542348969.61303627645071.096247823
2349211.98313661644997.2940543712349265.06743568644943.012036628
#Sta/Elev= 30
       0 2991.86    51.7 2990.68   106.7 2990.74   129.1 2989.84   176.6 2989.34
   198.5 2988.18   215.1 2988.74   241.3 2987.51   255.9 2988.21   271.9 2988.03
   284.1 2986.65   305.4 2988.32   337.4 2987.56  351.48 2985.93   354.1 2985.39
  360.55 2985.93   382.7  2987.1   400.1 2986.37   507.7 2985.15   521.3 2985.22
   533.4 2987.68   546.2 2986.49   555.8 2988.31   564.8 2987.57   570.5 2985.67
   586.9 2988.63   592.5 2991.13   598.6 2995.33     622  3014.8   634.7 3021.44
#Mann= 6, -1 ,  0
       0     0.1       0     300    0.08       0  351.48   0.045       0
  360.55    0.08       0  515.42    0.06       0  628.78     0.1       0
#XS Ineff= 2 , 0
          305.04 2989.68  558.86         2989.74
Permanent Ineff=
       F       F
Bank Sta=351.48,360.55
XS Rating Curve= 0 ,0
Exp/Cntr(USF)=0,0
Exp/Cntr=0.3,0.1

Type RM Length L Ch R = 1 ,174     ,,,
XS GIS Cut Line= 4
2348810.99893018645072.0978890582349143.30659923645131.583072128
2349268.22749538645082.6142377492349323.32486808645046.390683758
#Sta/Elev= 30
       0 2989.21    13.4 2987.84    41.8 2988.52    66.2 2986.95   110.9 2986.09
   151.5 2987.35   174.3 2985.89   212.5 2986.76   330.3 2985.27   338.5 2986.08
   342.8 2985.85  347.79 2983.91   351.4 2983.11  354.51 2983.92     360 2984.48
   389.5 2984.09   398.7 2985.59   414.2 2986.17   440.9 2985.71   458.8 2984.25
   463.1 2985.16   467.4 2987.06   471.7 2987.36   476.5 2987.05   484.3 2984.21
   487.2 2984.01   500.4 2987.56   505.2 2989.51   521.9 3001.59   537.7 3015.52
#Mann= 6, -1 ,  0
       0     0.1       0     160    0.08       0  347.79   0.045       0
  354.51    0.08       0  367.59    0.06       0  467.59     0.1       0
#XS Ineff= 2 , 0
                           472.2            2989
Permanent Ineff=
       F       F
Bank Sta=347.79,354.51
XS Rating Curve= 0 ,0
Exp/Cntr(USF)=0,0
Exp/Cntr=0.3,0.1
LCMann Table=0

Chan Stop Cuts=-1
Use User Specified Reach Order=0
Composite Channel Slope=5